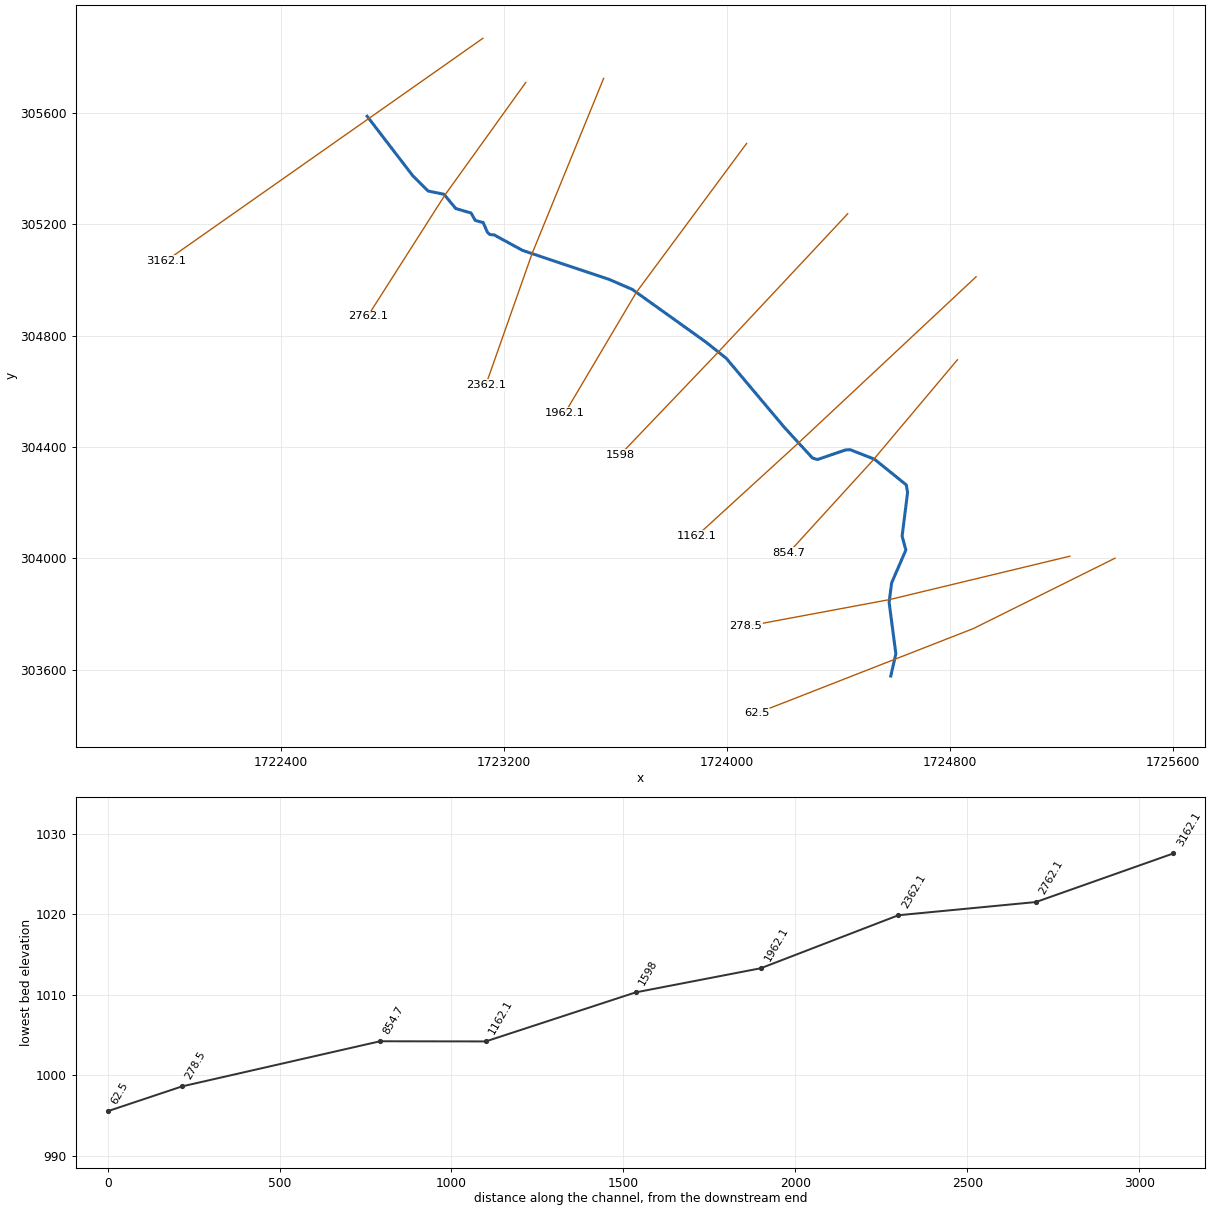
--- LmbrtRnT2.prj (project) ---

Proj Title=LmbrtRnT2
Current Plan=p01
Geom File=g01
Flow File=f01
Plan File=p01
DSS Export Rating Curves=0
DSS Export Rating Curve Sorted=0
DSS Export Volume Flow Curves=0
DXF OffsetX=0
DXF OffsetY=0
DXF ScaleX=0
DXF ScaleY=0

--- LmbrtRnT2.p01 (plan) ---

Plan Title=Floodplain
Program Version=4.00
Geom File=g01
Flow File=f01
K Sum by GR=0
Std Step Tol=0.01
Critical Tol=0.01
Num of Std Step Trials=20
Max Error Tol=0.3
Flow Tol Ratio=0.001
Split Flow NTrial=30
Split Flow Tol=0.02
Split Flow Ratio=0.02
Log Output Level=0
Friction Slope Method=1
Unsteady Friction Slope Method=2
Unsteady Bridges Friction Slope Method=1
Global Log Level=0
CheckData=False
Run HTab=0
Run UNet=0
Run PostProcess=0
UNET Theta=0
UNET Theta Warmup=0
UNET ZTol=0
UNET ZSATol=0
UNET MxIter=0
UNET MaxInSteps=0
UNET DtIC=0
UNET DtMin=0
UNET MaxCRTS=0
UNET WFStab=0
UNET SFStab=0
UNET WFX=0
UNET SFX=0
UNET DSS MLevel=0
UNET DZMax Abort=0
UNET Convert EG Bridges=0
UNET Use Existing IB Tables=0
UNET Froude Limit=0
UNET Froude Power=0
Write IC File=0
Echo Input=False
Echo Output=False
Write Detailed=0

--- LmbrtRnT2.f01 (steady flow) ---

Flow Title=NFF Regression Equation
Program Version=4.00
Number of Profiles=1
Profile Names=P100yr
River Rch & RM=LmbrtRnT2,Main      ,3162.1
768.1730
River Rch & RM=LmbrtRnT2,Main      ,1598
800.5936
River Rch & RM=LmbrtRnT2,Main      ,278.5
885.4690
River Rch & RM=LmbrtRnT2,Main      ,62.5
885.4690
Boundary for River Rch & Prof#=LmbrtRnT2,Main      ,1
Up Type=0
Dn Type=3
Dn Slope=0.005595

--- LmbrtRnT2.g01 (geometry) ---

Geom Title=USGS 3m DEM
Program Version=4.00

River Reach=LmbrtRnT2     ,Main
Reach XY= 30
     1722708.776      305588.503     1722872.352      305374.787
     1722927.486      305319.802     1722984.400      305308.109
     1723026.474      305256.853     1723081.376      305240.824
     1723096.649      305213.977     1723124.864      305206.412
     1723140.192      305171.590     1723149.128      305163.452
     1723164.114      305162.161     1723266.349      305106.291
     1723577.398      305001.843     1723659.432      304966.348
     1723923.142      304777.297     1723996.905      304718.405
     1724204.540      304470.948     1724306.058      304360.109
     1724323.501      304354.783     1724424.660      304389.261
     1724440.775      304390.226     1724528.063      304356.082
     1724642.145      304263.835     1724647.063      304236.838
     1724627.457      304079.414     1724640.852      304029.588
     1724589.859      303911.458     1724580.858      303841.421
     1724604.956      303656.478     1724586.726      303576.824

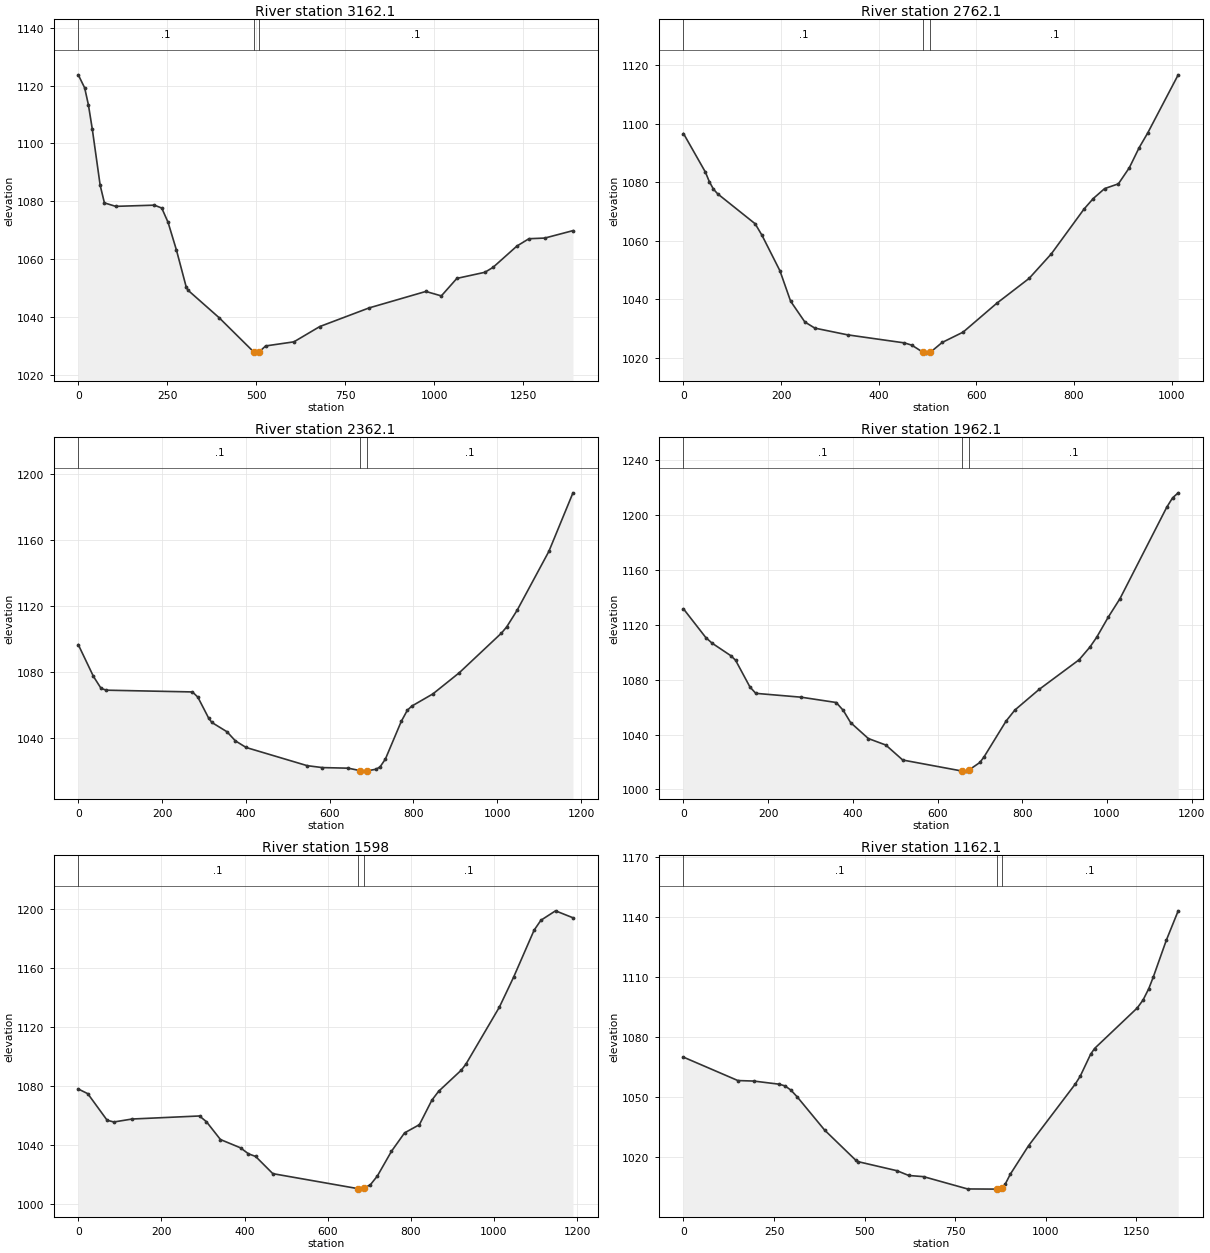
Type RM Length L Ch R = 1 ,3162.1,392.551,400,408.867
XS GIS Cut Line= 3
     1723123.704      305868.563     1722714.535      305580.328
     1721987.482      305068.706
#Sta/Elev= 30
       0 1123.69    17.9 1119.20    28.4 1113.36    39.3 1105.01    61.5 1085.52
    73.4 1079.45   105.1 1078.25   213.9 1078.66   234.5 1077.66   252.3 1072.69
   275.8 1063.12   303.4 1050.29   308.4 1049.25   395.5 1039.79     493 1027.93
   497.2 1027.54     508 1027.94   526.2 1030.02   605.7 1031.44   678.3 1036.72
   816.6 1043.15   976.3 1048.85  1019.8 1047.31  1063.4 1053.36  1142.1 1055.47
  1165.0 1057.17  1232.2 1064.55  1265.9 1067.07  1310.2 1067.29  1389.5 1069.86
#Mann= 3 , 0 , 0
       0     0.1       0     493   0.045       0     508     0.1       0
Bank Sta=     493,     508
Exp/Cntr=0.3,0.1

Type RM Length L Ch R = 1 ,2762.1,393.89,400,404.03
XS GIS Cut Line= 3
     1723277.668      305709.966     1722987.498      305305.034
     1722711.097      304870.272
#Sta/Elev= 30
       0 1096.59    44.9 1083.39    52.9 1080.13    61.4 1077.57    69.9 1075.98
   146.8 1065.73   160.9 1061.76   197.6 1049.64   219.4 1039.27   248.6 1032.15
   269.1 1030.05   336.2 1027.75   452.5 1025.00   467.7 1024.22   490.7 1021.79
   496.9 1021.50   505.7 1021.78   529.8 1025.14   572.8 1028.68   641.6 1038.53
   708.0 1047.05   753.4 1055.42   820.5 1070.76   839.4 1074.36   862.7 1077.76
   890.9 1079.39   913.4 1084.92   933.1 1091.65   951.2 1096.85  1013.4 1116.66
#Mann= 3 , 0 , 0
       0     0.1       0   490.7   0.045       0   505.7     0.1       0
Bank Sta=   490.7,   505.7
Exp/Cntr=0.3,0.1

Type RM Length L Ch R = 1 ,2362.1,405.64,400,395.587
XS GIS Cut Line= 3
     1723556.918      305724.626     1723300.117      305094.419
     1723134.233      304622.587
#Sta/Elev= 30
       0 1096.46    36.2 1077.21    54.5 1069.92    67.3 1068.87   272.5 1067.81
   285.3 1064.69   310.9 1052.10   318.6 1049.37   355.0 1043.68   375.0 1038.19
   400.7 1034.17   546.3 1023.17   582.7 1022.00   644.3 1021.65     673 1020.15
   682.7 1019.86     688 1019.97   710.9 1021.02   720.4 1022.46   733.0 1027.17
   770.8 1049.92   785.4 1056.74   796.0 1059.24   846.3 1066.61   909.2 1079.39
  1009.9 1103.40  1022.5 1107.18  1047.7 1117.38  1123.2 1152.93  1180.7 1188.37
#Mann= 3 , 0 , 0
       0     0.1       0     673   0.045       0     688     0.1       0
Bank Sta=     673,     688
Exp/Cntr=0.3,0.1

Type RM Length L Ch R = 1 ,1962.1,366.699,364.112,359.047
XS GIS Cut Line= 3
     1724069.728      305490.880     1723673.924      304955.214
     1723418.607      304522.935
#Sta/Elev= 30
       0 1131.67    52.6 1110.77    67.4 1106.67   111.7 1097.52   122.9 1094.23
   156.9 1074.69   170.7 1070.03   278.0 1067.22   360.6 1063.35   377.4 1057.55
   394.6 1048.70   436.4 1037.07   477.8 1032.31   517.7 1021.38   658.5 1013.30
   666.0 1013.28   673.5 1013.99   699.8 1019.59   709.6 1023.64   761.6 1049.76
   782.5 1057.86   839.6 1072.87   934.2 1094.55   959.7 1103.81   975.6 1110.92
  1003.1 1125.70  1030.7 1139.15  1141.0 1205.78  1154.8 1212.65  1168.1 1216.34
#Mann= 3 , 0 , 0
       0     0.1       0   658.5   0.045       0   673.5     0.1       0
Bank Sta=   658.5,   673.5
Exp/Cntr=0.3,0.1

Type RM Length L Ch R = 1 ,1598,437.389,435.888,434.276
XS GIS Cut Line= 3
     1724432.272      305238.053     1723962.963      304735.548
     1723616.045      304371.655
#Sta/Elev= 30
       0 1078.13    22.9 1074.95    69.4 1056.96    85.6 1055.78   129.6 1057.79
   291.7 1059.85   308.5 1055.92   342.1 1043.88   390.5 1038.25   409.3 1034.24
   426.8 1032.41   468.1 1020.77     672 1010.66   678.1 1010.28     687 1010.80
   703.1 1013.34   719.5 1019.11   753.6 1035.93   785.1 1048.39   820.8 1053.96
   850.7 1070.51   867.1 1076.59   921.6 1090.91   932.7 1094.97  1013.2 1133.59
  1047.6 1153.99  1096.8 1185.76  1113.2 1192.48  1148.3 1198.86  1190.3 1194.16
#Mann= 3 , 0 , 0
       0     0.1       0     672   0.045       0     687     0.1       0
Bank Sta=     672,     687
Exp/Cntr=0.3,0.1

Type RM Length L Ch R = 1 ,1162.1,304.213,307.371,310.024
XS GIS Cut Line= 3
     1724892.608      305011.463     1724256.027      304414.734
     1723892.219      304081.523
#Sta/Elev= 30
       0 1070.09   150.1 1058.41   194.2 1058.15   264.0 1056.59   280.3 1055.74
   296.6 1053.63   314.2 1050.21   389.8 1033.65   475.6 1018.64   482.2 1017.90
   589.5 1013.38   622.0 1011.00   662.9 1010.42   784.4 1004.28     865 1004.20
   868.6 1004.19     880 1004.79   888.8 1006.84   902.2 1011.59   952.6 1025.84
  1082.1 1056.75  1095.5 1060.62  1123.8 1071.43  1134.9 1074.40  1252.6 1094.61
  1268.7 1098.56  1284.8 1104.34  1297.2 1110.13  1333.1 1128.46  1365.9 1143.16
#Mann= 3 , 0 , 0
       0     0.1       0     865   0.045       0     880     0.1       0
Bank Sta=     865,     880
Exp/Cntr=0.3,0.1

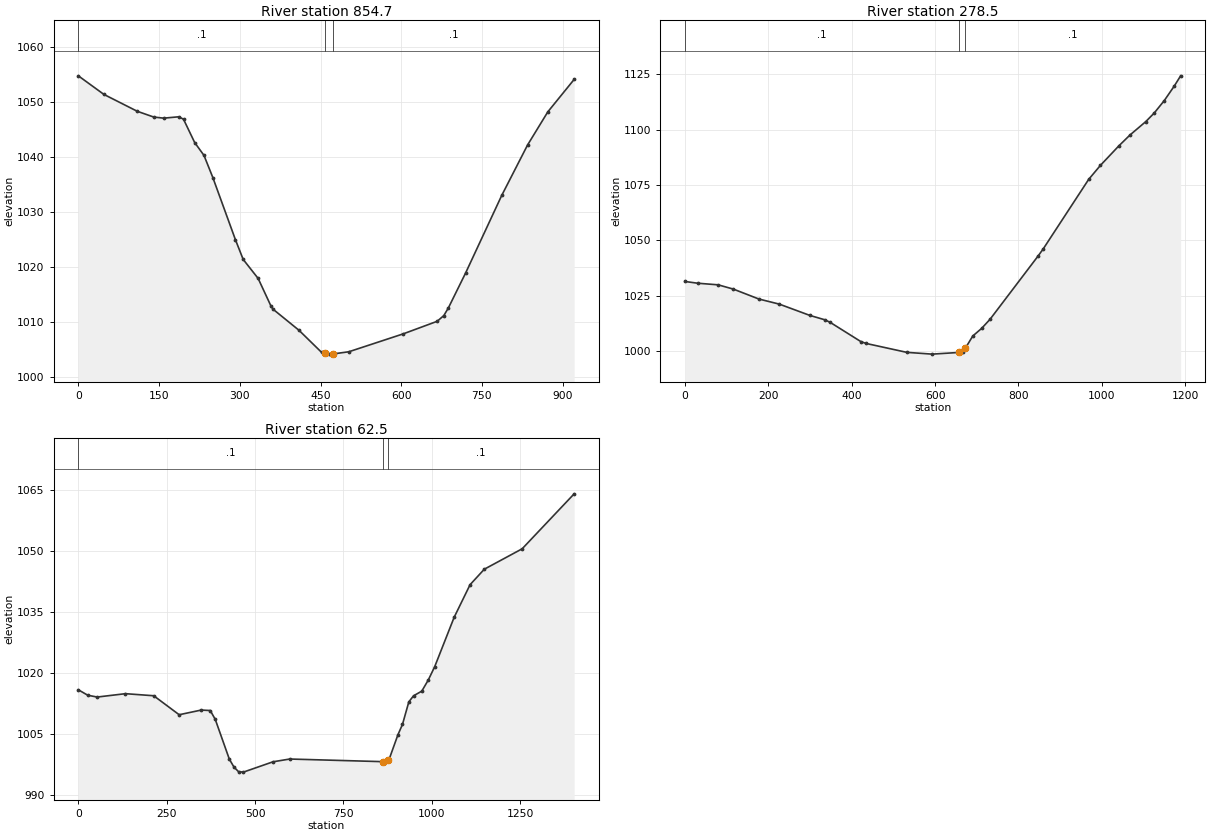
Type RM Length L Ch R = 1 ,854.7,590.797,576.247,561.068
XS GIS Cut Line= 3
     1724825.680      304713.207     1724520.693      304349.793
     1724219.993      304019.236
#Sta/Elev= 30
       0 1054.84    47.5 1051.46   109.5 1048.39   140.1 1047.34   158.6 1047.14
   187.0 1047.39   195.5 1046.93   216.2 1042.70   233.5 1040.36   249.9 1036.34
   292.0 1025.00   306.3 1021.44   334.1 1017.98   357.5 1013.05   361.7 1012.39
   410.0 1008.55   452.1 1004.52   457.9 1004.38   466.0 1004.21   472.9 1004.24
   502.6 1004.64   603.5 1007.89   666.7 1010.18   679.1 1011.22   687.5 1012.60
   719.7 1018.99   786.7 1033.08   834.8 1042.27   872.4 1048.29   921.3 1054.19
#Mann= 3 , 0 , 0
       0     0.1       0   457.9   0.045       0   472.9     0.1       0
Bank Sta=   457.9,   472.9
Exp/Cntr=0.3,0.1

Type RM Length L Ch R = 1 ,278.5,212.158,215.953,221.482
XS GIS Cut Line= 3
     1725228.916      304007.310     1724582.471      303851.414
     1724067.686      303755.165
#Sta/Elev= 30
       0 1031.45    30.8 1030.65    80.0 1029.92   116.6 1027.98   177.7 1023.50
   226.6 1021.20   299.8 1016.10   336.1 1014.10   348.7 1012.94   422.0 1004.28
   434.2 1003.45   531.9  999.41   592.9  998.60   657.8  999.36   666.2  999.38
   672.8 1001.33   690.4 1006.79   711.6 1010.23   731.9 1014.37   847.4 1043.05
   859.5 1046.22   968.2 1077.57   996.5 1083.93  1040.6 1092.73  1067.7 1097.71
  1105.1 1103.69  1125.2 1107.54  1149.6 1113.22  1173.5 1119.78  1188.7 1124.39
#Mann= 3 , 0 , 0
       0     0.1       0   657.8   0.045       0   672.8     0.1       0
Bank Sta=   657.8,   672.8
Exp/Cntr=0.3,0.1

Type RM Length L Ch R = 1 ,62.5,78.202,62.538,46.432
XS GIS Cut Line= 3
     1725391.107      304000.154     1724883.067      303747.327
     1724105.199      303442.464
#Sta/Elev= 30
       0 1015.82    26.8 1014.47    53.4 1014.03   133.4 1014.86   213.3 1014.35
   285.3 1009.67   347.6 1010.82   373.2 1010.71   387.4 1008.53   427.2  998.73
   440.4  996.76   453.2  995.64   467.0  995.52   550.9  998.07   598.3  998.75
   861.5  998.10   876.5  998.48   878.9  998.57   904.4 1004.76   917.1 1007.27
   935.1 1012.84   948.5 1014.34   971.8 1015.49   990.1 1018.22  1008.4 1021.53
  1063.4 1033.70  1108.4 1041.73  1148.6 1045.54  1255.8 1050.58  1402.9 1064.13
#Mann= 3 , 0 , 0
       0     0.1       0   861.5   0.045       0   876.5     0.1       0
Bank Sta=   861.5,   876.5
Exp/Cntr=0.3,0.1